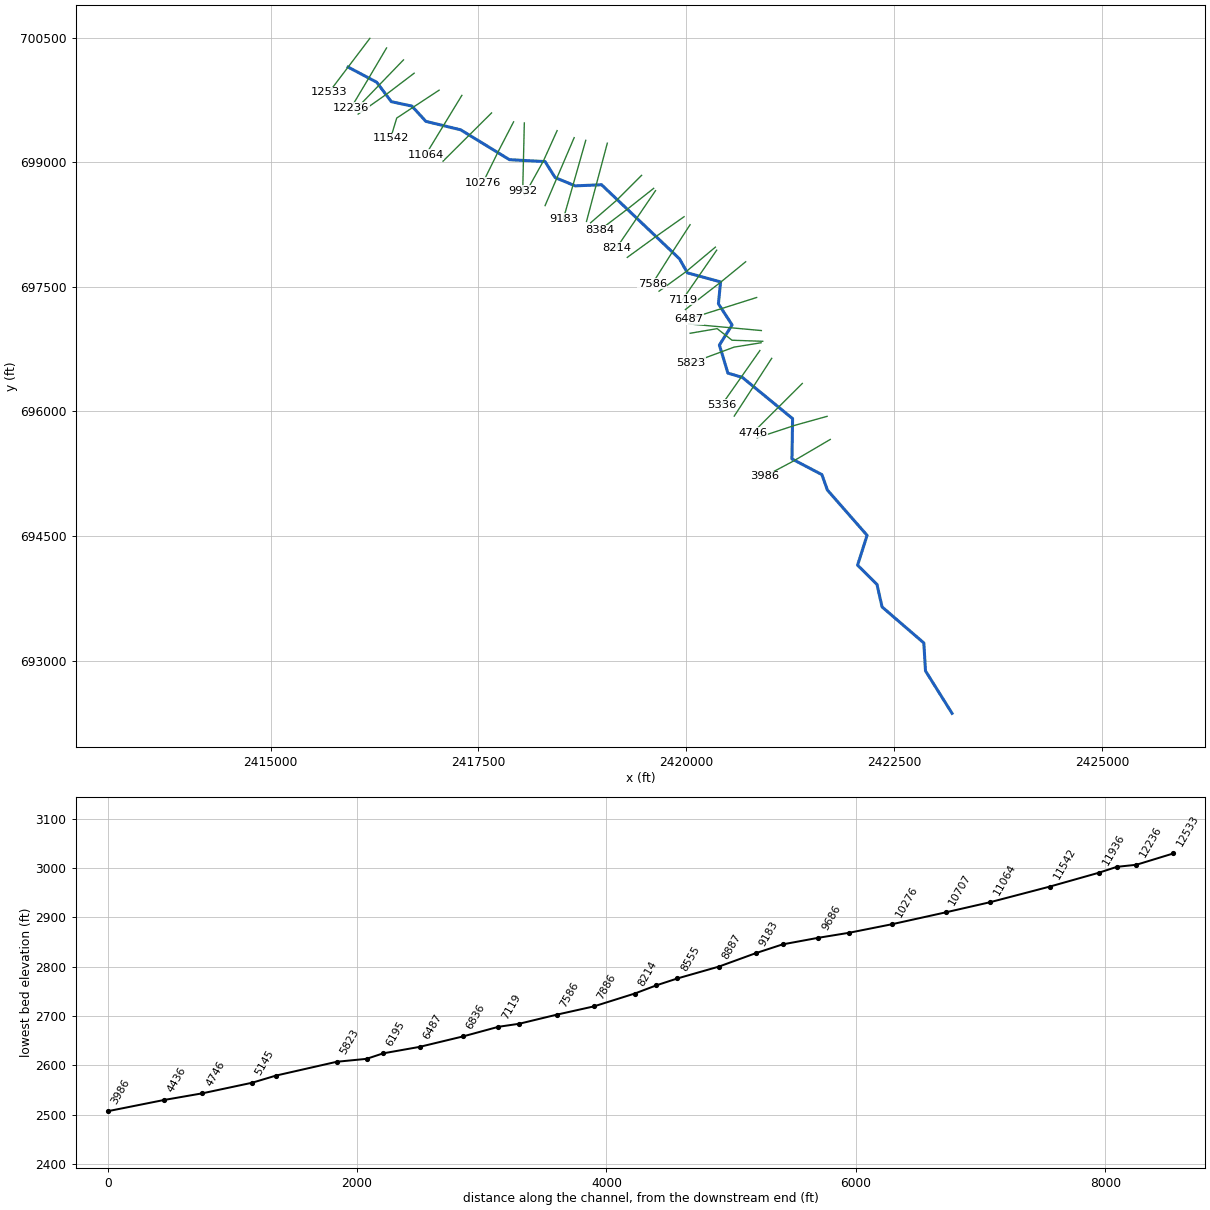
--- LONGRN.prj (project) ---

Proj Title=LONGRN
Current Plan=p01
Default Exp/Contr=0,0
English Units
Geom File=g01
Flow File=f01
Plan File=p01
BEGIN DESCRIPTION:
Stream Name: Long Run
Flood Zone: Approximate
Pendleton County, West Virginia
HEC-RAS Version: 5.0.7
Hydrology Method:
Regression equation
END DESCRIPTION:
DSS Export Rating Curves= 0
DSS Export Rating Curve Sorted= 0
DSS Export Volume Flow Curves= 0
DXF OffsetX= 0
DXF OffsetY= 0
DXF ScaleX= 0
DXF ScaleY= 0

--- LONGRN.p01 (plan) ---

Plan Title=Floodplain
Program Version=5.07
Short Identifier=Floodplain
Geom File=g01
Flow File=f01
Subcritical Flow
K Sum by GR= 0
Std Step Tol= 0.01
Critical Tol= 0.01
Num of Std Step Trials= 20
Max Error Tol= 0.3
Flow Tol Ratio= 0.001
Split Flow NTrial= 30
Split Flow Tol= 0.02
Split Flow Ratio= 0.02
Log Output Level= 0
Friction Slope Method= 1
Unsteady Friction Slope Method= 2
Unsteady Bridges Friction Slope Method= 1
Parabolic Critical Depth
Global Vel Dist= 0 , 0 , 0
Global Log Level= 0
CheckData=True
Encroach Param=-1 ,0,0, 0
Mapping Interval=1HOUR
Computation Time Step Use Courant=        0
Computation Time Step Use Time Series=    0
Computation Time Step Count To Double=0
Computation Time Step Max Doubling=0
Computation Time Step Max Halving=0
Computation Time Step Residence Courant=0
Run HTab= 0
Run UNet= 0
Run Sediment= 0
Run PostProcess= 0
Run WQNet= 0
Run RASMapper= 0
UNET Theta= 0
UNET Theta Warmup= 0
UNET ZTol= 0
UNET ZSATol= 0
UNET MxIter= 0
UNET Max Iter WO Improvement= 0
UNET MaxInSteps= 0
UNET DtIC= 0
UNET DtMin= 0
UNET MaxCRTS= 0
UNET WFStab= 0
UNET SFStab= 0
UNET WFX= 1
UNET SFX= 1
UNET 1D Methodology=Finite Difference
UNET DSS MLevel= 1
UNET Pardiso=0
UNET DZMax Abort= 0
UNET Use Existing IB Tables= 0
UNET Froude Reduction=False
UNET Froude Limit= 0
UNET Froude Power= 0
UNET D1 Cores= 0
UNET D2 Coriolis=0
UNET D2 Cores= 0
UNET D2 Theta= 1
UNET D2 Theta Warmup= 1
UNET D2 Z Tol= 0.01
UNET D2 Volume Tol= 0.01
UNET D2 Max Iterations= 20
UNET D2 Equation= 0
UNET D2 RampUpFraction=0.1
UNET D2 TimeSlices= 1
UNET D2 BCVolumeCheck=0
UNET D1D2 MaxIter= 0
UNET D1D2 ZTol=0.01
UNET D1D2 QTol=0.1
UNET D1D2 MinQTol=1
Write IC File= 0
Write IC File at Fixed DateTime=0
Write IC File at Sim End=0
Echo Input=False
Echo Parameters=False
Echo Output=False
Write Detailed= 0
HDF Write Warmup=0
HDF Write Time Slices=0
HDF Flush=0
HDF Face Node Velocities=0
HDF Compression= 1
HDF Chunk Size= 1
HDF Spatial Parts= 1
HDF Use Max Rows=0
HDF Fixed Rows= 1
Calibration Method= 0
Calibration Iterations= 20
Calibration Max Change=0.05
Calibration Tolerance=0.2
Calibration Maximum=1.5
Calibration Minimum=0.5
Calibration Optimization Method= 1
WQ AD Non Conservative
WQ ULTIMATE=-1
WQ Max Comp Step=1HOUR
WQ Output Interval=15MIN
WQ Output Selected Increments= 0
WQ Output face flow=0
WQ Output face velocity=0
WQ Output face area=0
WQ Output face dispersion=0
WQ Output cell volume=0
WQ Output cell surface area=0
WQ Output cell continuity=0
WQ Output cumulative cell continuity=0
WQ Output face conc=0
WQ Output face dconc_dx=0
WQ Output face courant=0
WQ Output face peclet=0
WQ Output face adv mass=0
WQ Output face disp mass=0
WQ Output cell mass=0
WQ Output cell source sink temp=0
WQ Output nsm pathways=0
WQ Output nsm derived pathways=0
WQ Output MaxMinRange=-1
WQ Daily Max Min Mean=-1
WQ Daily Range=0
WQ Daily Time=0
WQ Create Restart=0
WQ Fixed Restart=0
WQ System Summary=0
WQ Write To DSS=0
WQ Use Fixed Temperature=0
Sorting and Armoring Iterations= 10
XS Update Threshold= 0.02
Bed Roughness Predictor= 0
Hydraulics Update Threshold= 0.02
Energy Slope Method= 1
Volume Change Method= 1
Sediment Retention Method= 0
XS Weighting Method= 0
Number of US Weighted Cross Sections= 1
Number of DS Weighted Cross Sections= 1
Upstream XS Weight=0
Main XS Weight=1
Downstream XS Weight=0
Number of DS XS's Weighted with US Boundary= 1
Upstream Boundary Weight= 1
Weight of XSs Associated with US Boundary= 0
Number of US XS's Weighted with DS Boundary= 1
Downstream Boundary Weight= 0.5
Weight of XSs Associated with DS Boundary= 0.5
Percentile Method= 0
Sediment Output Level= 3
Mass or Volume Output= 0
Output Increment Type= 1
Profile and TS Output Increment= 1
XS Output Flag= 0
XS Output Increment= 10
Write Gradation File= 0
Read Gradation Hotstart= 0
Write HDF5 File= 1
Write Binary Output= 1
Write DSS Sediment File= 0
SV Curve= 0
Specific Gage Flag= 0

--- LONGRN.f01 (steady flow) ---

Flow Title=Flows
Program Version=5.07
Number of Profiles= 6
Profile Names=P100yr,P10yr,P25yr,P50yr,P500yr,P101yr
River Rch & RM=LONGRN,Main            ,12533
     807     376     532     665    1187     982
River Rch & RM=LONGRN,Main            ,10276
     900     418     593     742    1325    1095
River Rch & RM=LONGRN,Main            ,8887
    1005     466     661     828    1482    1223
River Rch & RM=LONGRN,Main            ,6836
    1146     531     754     944    1693    1395
River Rch & RM=LONGRN,Main            ,3986
    1278     591     839    1052    1889    1555
River Rch & RM=LONGRN,Main            ,0
    1790     823    1173    1472    2656    2179
Boundary for River Rch & Prof#=LONGRN,Main            , 1
Up Type= 0
Dn Type= 1
Dn Known WS=2293.66
Boundary for River Rch & Prof#=LONGRN,Main            , 2
Up Type= 0
Dn Type= 1
Dn Known WS=2291.96
Boundary for River Rch & Prof#=LONGRN,Main            , 3
Up Type= 0
Dn Type= 1
Dn Known WS=2292.64
Boundary for River Rch & Prof#=LONGRN,Main            , 4
Up Type= 0
Dn Type= 1
Dn Known WS=2293.15
Boundary for River Rch & Prof#=LONGRN,Main            , 5
Up Type= 0
Dn Type= 1
Dn Known WS=2294.85
Boundary for River Rch & Prof#=LONGRN,Main            , 6
Up Type= 0
Dn Type= 1
Dn Known WS=2294.21
DSS Import GetInterval= 0
DSS Import GetPeak= 0
DSS Import FillOption= 0

--- LONGRN.g01 (geometry) ---

Geom Title=Geometry
Program Version=5.07

River Reach=LONGRN          ,Main
Reach XY= 30
     2415931.719      700145.547     2416275.332      699963.416
     2416451.747      699728.882     2416698.783      699676.132
     2416867.082      699492.124     2417285.626      699390.434
     2417872.575      699030.782     2418301.435      699007.869
     2418421.946      698815.622     2418664.203      698715.461
     2418980.771      698729.014     2419918.494      697836.951
      2420012.86      697668.342     2420412.682       697559.27
     2420386.563      697295.745     2420551.176      697041.551
     2420398.495      696798.994     2420500.842      696461.634
     2420674.965      696409.486      2421278.95      695913.403
     2421271.426      695428.207     2421631.285      695239.554
     2421697.658      695053.973     2422175.269      694508.674
     2422060.567      694148.976     2422294.053       693917.95
     2422355.362      693646.601     2422857.728      693213.129
     2422877.922      692876.613       2423197.7      692365.156

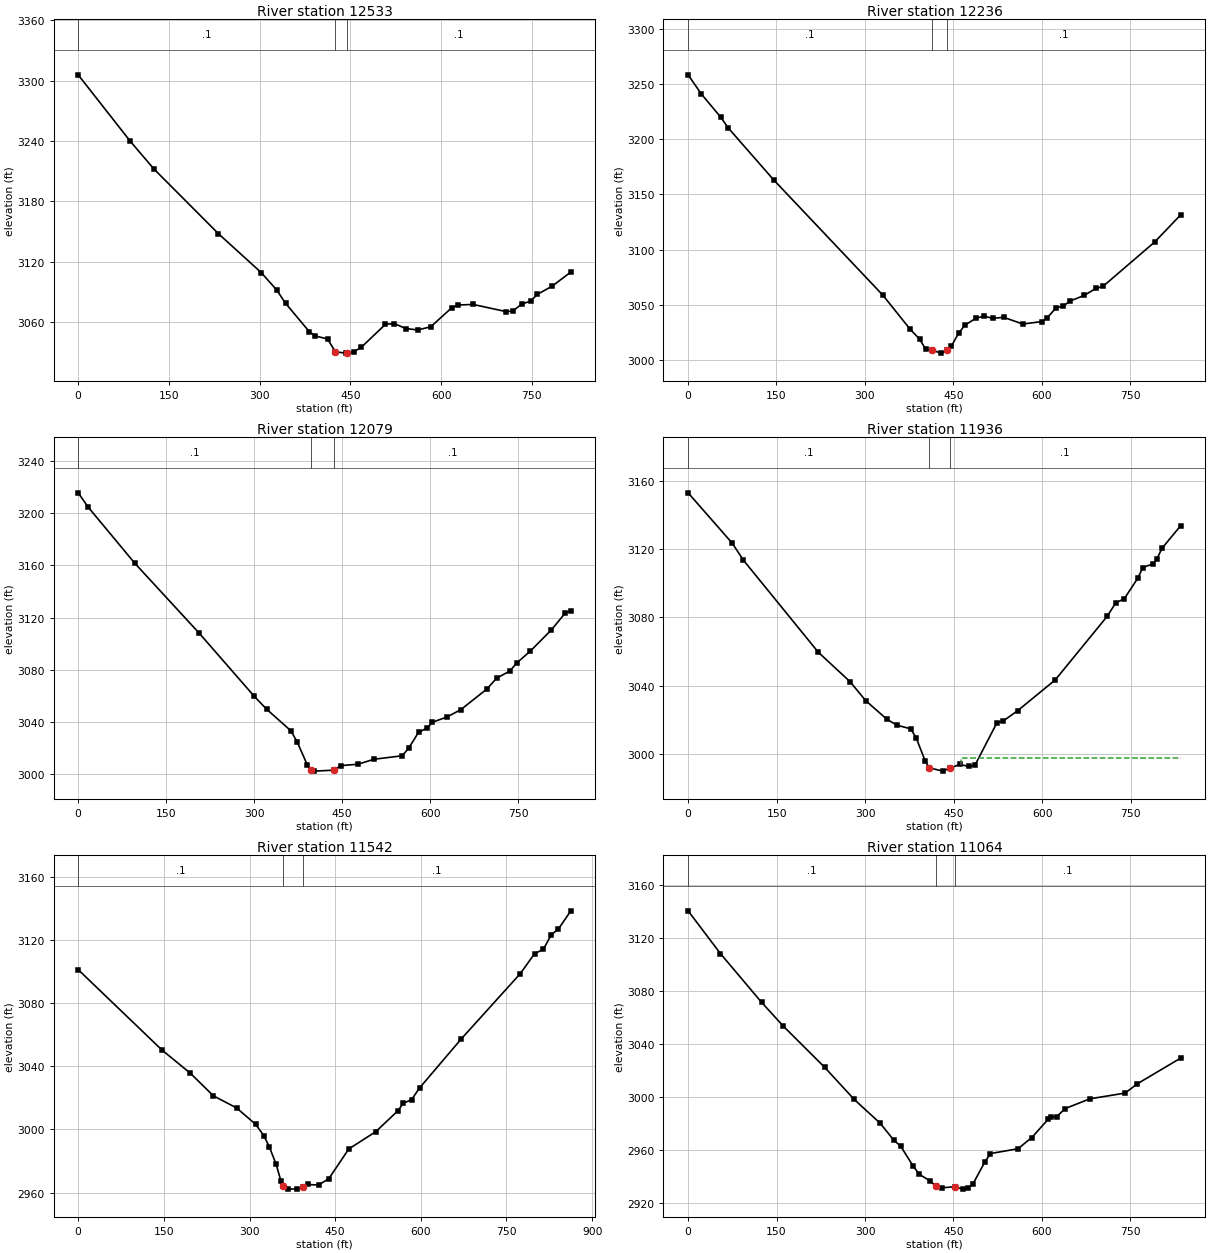
Type RM Length L Ch R = 1 ,12533   ,297.1,297.1,297.1
XS GIS Cut Line= 2
2416193.84784425700491.5213236432415701.93812368 699842.26758208
#Sta/Elev= 30
       0 3305.74    86.1  3239.8   125.4 3212.14   231.6 3148.12   302.5 3109.41
   328.2 3092.09   342.9 3078.82   382.4 3050.48   392.2 3046.37   412.3 3043.45
   425.2 3030.68   442.3 3029.35   444.4 3029.35   455.5 3030.65   468.1 3035.13
     508 3057.95   522.7 3058.69   541.7 3053.76   561.5 3052.37   582.9 3055.51
   618.1 3074.64   628.1 3077.16   653.2 3077.67   707.2 3070.64   718.4 3071.09
   733.5  3078.1   747.9 3080.96   759.3 3087.71   783.7 3095.88   814.6 3109.91
#Mann= 3 , 0 , 0
       0      .1       0   425.2    .045       0   444.4      .1       0
Bank Sta=425.2,444.4
XS Rating Curve= 0 ,0
Exp/Cntr(USF)=0,0
Exp/Cntr=0.3,0.1

Type RM Length L Ch R = 1 ,12236   ,162.2,156.6,153.6
XS GIS Cut Line= 3
2416394.28198263700375.801017371     2416176.399      700006.392
     2415967.829      699656.661
#Sta/Elev= 30
       0 3258.13    22.7 3240.62    55.8 3219.57    67.5 3210.45     145 3163.21
   330.8 3058.58     377 3027.82   392.8 3019.06   403.4  3009.7   414.4 3009.02
   428.9 3006.33   439.9 3009.01   446.9 3012.65   458.9 3024.32   470.2  3031.8
   488.8 3037.99   502.4 3039.79   516.8 3037.77   535.4 3038.73     568 3032.68
   600.6 3034.89   609.9 3038.56   623.9 3047.03   636.9 3049.01   648.5 3053.54
   671.9 3058.48   692.3 3064.97     704 3066.67   791.6 3106.79   836.1 3131.49
#Mann= 3 ,-1 , 0
       0      .1       0   414.4    .045       0   439.9      .1       0
Bank Sta=414.4,439.9
XS Rating Curve= 0 ,0
Exp/Cntr=0.3,0.1

Type RM Length L Ch R = 1 ,12079   ,147.3,143.4,140.2
XS GIS Cut Line= 2
2416598.01914324700232.1346861272416014.79533302 699628.13852102
#Sta/Elev= 30
       0 3215.72    17.3 3204.59    96.5 3161.67   206.3 3107.98   300.2 3059.47
   321.4 3049.57   362.5 3033.07   373.3 3024.45   390.7 3006.66   396.5 3002.65
     402 3002.13     436 3002.87   447.3 3006.36   476.9 3007.42   503.9 3011.23
   552.2 3013.91   563.3 3019.79     580 3031.86   594.4 3035.12   603.6 3039.64
   628.4 3043.65   652.3 3049.38   696.8 3065.25   713.2 3073.51   735.7 3078.95
   747.2 3085.06   770.6 3094.27   806.6 3110.62   830.2 3123.56   839.6  3125.4
#Mann= 3 ,-1 , 0
       0      .1       0   396.5    .045       0     436      .1       0
Bank Sta=396.5,436
XS Rating Curve= 0 ,0
Exp/Cntr(USF)=0,0
Exp/Cntr=0.3,0.1

Type RM Length L Ch R = 1 ,11936   ,398.8,393.7,395.9
XS GIS Cut Line= 3
2416726.24605211700071.617051321     2416393.521       699818.58
     2416052.716      699579.416
#Sta/Elev= 30
       0 3152.83    74.8  3123.4    93.7 3113.47   220.5  3059.7   274.2 3042.52
   300.9  3031.4     337 3020.44   354.1 3017.05     377 3014.96   386.3 3009.66
   401.4 2996.29   408.4 2992.18   431.4 2990.25   442.8  2991.9     460 2994.16
   475.2    2993   485.8 2993.68   523.2 3018.63   533.8 3019.56   558.2 3025.58
   621.8 3043.55   709.8 3080.71   724.4 3088.62   738.5 3090.85   761.5 3102.93
   770.1 3109.19   787.9 3111.45   793.5 3113.89   802.6 3120.44   834.4  3133.7
#Mann= 3 ,-1 , 0
       0      .1       0   408.4    .045       0   442.8      .1       0
#XS Ineff= 2 , 0
       0                   462.9       0    2998
Permanent Ineff=
       F       F
Bank Sta=408.4,442.8
XS Rating Curve= 0 ,0
Exp/Cntr=0.3,0.1

Type RM Length L Ch R = 1 ,11542   ,464.5,478.4,479.2
XS GIS Cut Line= 3
2417026.26743509699867.3952456242416516.85018249699532.034072096
     2416443.419      699290.147
#Sta/Elev= 30
       0 3101.19   146.4 3050.38   196.4 3035.56   236.8 3021.24   277.3 3013.61
   310.7 3003.22   325.1 2996.03   334.7  2988.9   346.6 2977.96   355.2 2967.05
   358.6 2964.01   366.8 2962.29   382.5 2962.15   393.7 2963.72   401.7 2965.09
   420.9 2964.74     439 2968.82   473.8 2987.58   521.4 2998.62   559.7 3011.74
   569.3 3016.53   583.7 3018.83     598 3026.33   670.2 3057.05   774.1 3098.63
   799.2 3111.29   814.5 3114.03   828.5 3123.31     841 3126.96   862.7 3138.43
#Mann= 3 ,-1 , 0
       0      .1       0   358.6    .045       0   393.7      .1       0
Bank Sta=358.6,393.7
XS Rating Curve= 0 ,0
Exp/Cntr=0.3,0.1

Type RM Length L Ch R = 1 ,11064   ,362.7,356.8,352
XS GIS Cut Line= 2
 2417300.1535734699804.7716110422416865.67564757699091.178393962
#Sta/Elev= 30
       0 3140.82    54.8 3108.52   124.6 3071.67   161.4 3053.72   231.7  3022.5
   281.8 2998.26   325.8 2980.27   348.6 2967.63   360.6  2962.9   381.5 2948.01
   392.4 2941.58   409.6 2936.99   420.5 2932.55   430.3 2931.51   451.8 2932.31
   465.8 2930.52   475.2 2931.38   482.7 2934.13   503.1 2950.94   512.7  2957.4
   559.5 2961.05   582.9 2969.53     611  2983.5   615.7 2984.98   625.1 2985.26
   639.1 2991.33   681.3 2998.76   741.1  3003.1   762.1  3010.2   835.5 3029.59
#Mann= 3 ,-1 , 0
       0      .1       0   420.5    .045       0   451.8      .1       0
Bank Sta=420.5,451.8
XS Rating Curve= 0 ,0
Exp/Cntr=0.3,0.1

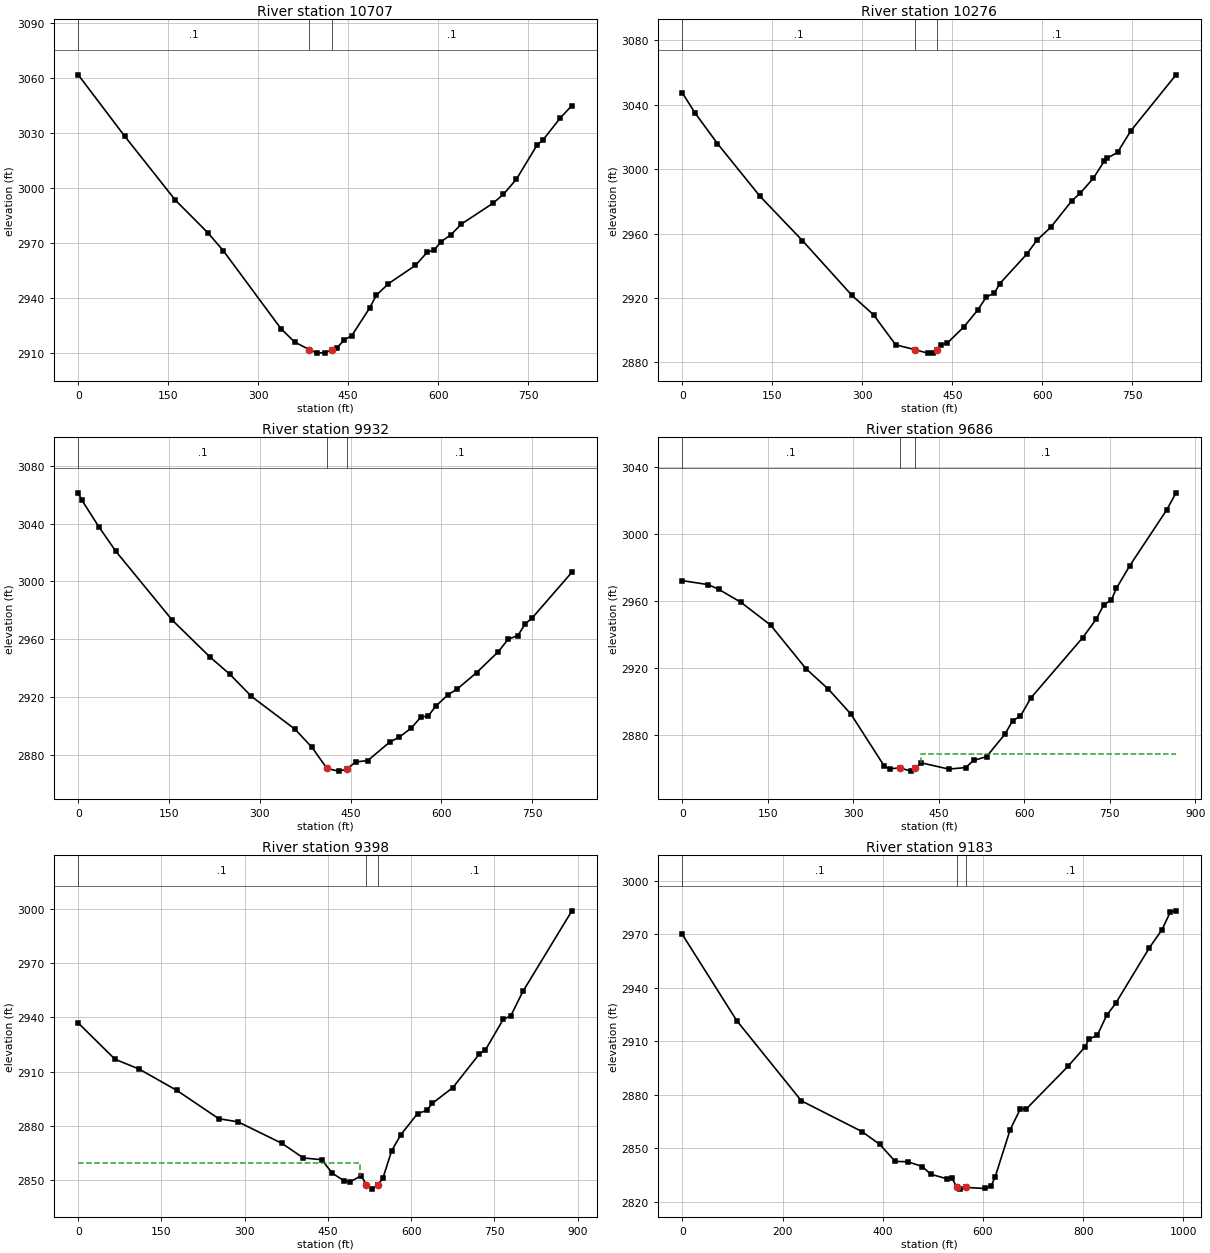
Type RM Length L Ch R = 1 ,10707   ,416.2,431.2,431.6
XS GIS Cut Line= 2
2417657.33141754699593.3130350962417073.81438913699012.982337184
#Sta/Elev= 30
       0 3061.51    77.2  3028.2   161.9 2993.25   215.7 2975.58   241.7 2965.76
   338.1 2923.17   360.8 2915.91   385.4 2911.78   398.5 2909.89   411.8 2910.19
   423.2 2911.71   430.6 2912.46   443.7 2917.17   456.1 2919.43   485.6 2934.35
   496.9 2941.37     517 2947.69   562.1  2957.7     582 2964.93   593.4 2966.05
   604.7 2970.53   621.7 2974.49   638.7  2980.2   690.9 2991.43   708.8 2996.37
   730.5 3004.66   765.2  3023.4   774.9 3026.04   803.2 3037.86     823 3044.75
#Mann= 3 ,-1 , 0
       0      .1       0   385.4    .045       0   423.2      .1       0
Bank Sta=385.4,423.2
XS Rating Curve= 0 ,0
Exp/Cntr=0.3,0.1

Type RM Length L Ch R = 1 ,10276   ,330.1,343.7,346.5
XS GIS Cut Line= 3
     2417922.566      699486.0292417736.64591052      699126.088
     2417551.932       698751.48
#Sta/Elev= 30
       0 3047.19    21.5 3034.58    58.6 3015.74   129.6 2983.02   200.1 2955.63
   282.7 2921.61   318.7 2909.59   355.5 2890.98   388.1 2887.93   408.7 2885.81
   417.6 2885.99   423.9 2887.78     431 2890.85   441.8 2892.11   469.6 2902.22
   492.6 2912.68   506.8 2920.67   520.2 2923.08   529.1 2928.95   573.7 2947.05
   591.1 2955.93   613.8 2963.76   649.5 2980.43   662.7 2984.83   685.2 2994.34
     703 3004.78   707.5 3006.59   725.3 3010.29   747.6 3023.74   822.8 3058.41
#Mann= 3 ,-1 , 0
       0      .1       0   388.1    .045       0   423.9      .1       0
Bank Sta=388.1,423.9
XS Rating Curve= 0 ,0
Exp/Cntr=0.3,0.1

Type RM Length L Ch R = 1 ,9932    ,252.9,246.1,241.7
XS GIS Cut Line= 2
2418051.80172675 699473.013693062418032.32424158698657.688886321
#Sta/Elev= 30
       0 3061.36     6.1 3056.22    34.4 3037.61    62.1 3020.87   155.5 2973.06
   218.3 2947.33   250.2 2935.74   286.2 2920.27   358.2 2897.52   386.1 2885.01
     411 2870.33   430.2 2868.49   443.8 2869.86   458.3 2874.86   478.3 2875.78
   514.3  2888.5   530.7 2892.12   550.4 2898.42   566.3 2906.05   578.3 2906.68
   590.3 2913.34   610.3 2921.24   626.3 2925.45   658.3 2936.82   694.3 2951.38
   710.3 2959.94   726.3 2962.41   738.3  2970.4   750.3  2974.8   815.6 3006.33
#Mann= 3 ,-1 , 0
       0      .1       0     411    .045       0   443.8      .1       0
Bank Sta=411,443.8
XS Rating Curve= 0 ,0
Exp/Cntr=0.3,0.1

Type RM Length L Ch R = 1 ,9686    ,289.5,287.2,288.5
XS GIS Cut Line= 3
2418446.22271742699380.534193666     2418281.188      699015.357
      2418055.25      698608.145
#Sta/Elev= 30
       0 2972.11    45.7 2969.74    64.3 2966.86   102.8 2959.19     155 2945.53
   216.9 2919.58   256.4 2907.29   295.9  2892.4   354.6 2861.24   363.6 2859.72
   381.8 2860.33   400.7 2858.36   408.2 2860.04   419.6 2863.28   467.6 2859.58
   497.3 2860.49   511.1 2864.72   533.9 2867.01     566 2880.37   579.7 2888.43
   593.4 2891.22   611.7 2902.07   702.6 2938.06   726.1 2948.97   739.8 2957.73
     753 2960.57   761.8 2967.53   785.3 2981.07   850.1 3014.38   866.4 3024.56
#Mann= 3 ,-1 , 0
       0      .1       0   381.8    .045       0   408.2      .1       0
#XS Ineff= 2 , 0
                          419.42         2868.81
Permanent Ineff=
       F       F
Bank Sta=381.8,408.2
XS Rating Curve= 0 ,0
Exp/Cntr=0.3,0.1

Type RM Length L Ch R = 1 ,9398    ,213.7,215.5,216.2
XS GIS Cut Line= 2
2418651.28652991699295.7808428662418301.35224378698477.669635102
#Sta/Elev= 30
       0 2936.82    66.2 2916.81   109.7 2911.35   177.8 2899.54   253.3  2883.9
   288.1 2882.16   367.5 2870.21   405.6 2862.19   438.7 2861.25   458.2 2853.69
   479.5 2849.53   489.6 2848.93     510 2852.38   519.1 2847.43   530.3 2844.96
   540.4 2847.43   540.4 2847.44   549.1 2850.95   564.8 2866.04   581.1 2874.92
   611.6 2886.73   628.8 2888.55   637.9 2892.33   675.3 2901.13   723.2 2919.79
   733.7 2921.81   765.9 2938.76   779.7 2940.82   801.5 2954.29   889.8 2998.85
#Mann= 3 ,-1 , 0
       0      .1       0   519.1    .045       0   540.4      .1       0
#XS Ineff= 2 , 0
          508.13 2859.18
Permanent Ineff=
       F       F
Bank Sta=519.1,540.4
XS Rating Curve= 0 ,0
Exp/Cntr(USF)=0,0
Exp/Cntr=0.3,0.1

Type RM Length L Ch R = 1 ,9183    ,303.9,295.8,293.9
XS GIS Cut Line= 2
 2418790.6777307699263.5475833292418520.78759397698315.841930741
#Sta/Elev= 30
       0 2969.81   108.8 2921.45   237.7 2876.58   358.4  2859.4   394.1  2852.2
   424.9 2842.63   449.9 2842.49     479 2839.78   495.8 2835.48   528.1 2832.92
   537.8  2833.5   547.7 2828.25   554.7 2827.13   566.3 2828.05   603.7 2827.51
   616.2  2828.7   624.5 2834.07   654.4 2860.47   674.4 2871.92   686.9 2872.15
   770.1 2896.03   803.4 2906.68   811.7 2911.21   828.3 2913.31   846.8 2924.45
   864.8 2931.15   932.3 2962.41   957.3 2972.41   973.9 2982.38   985.4 2983.06
#Mann= 3 ,-1 , 0
       0      .1       0   547.7    .045       0   566.3      .1       0
Bank Sta=547.7,566.3
XS Rating Curve= 0 ,0
Exp/Cntr=0.3,0.1

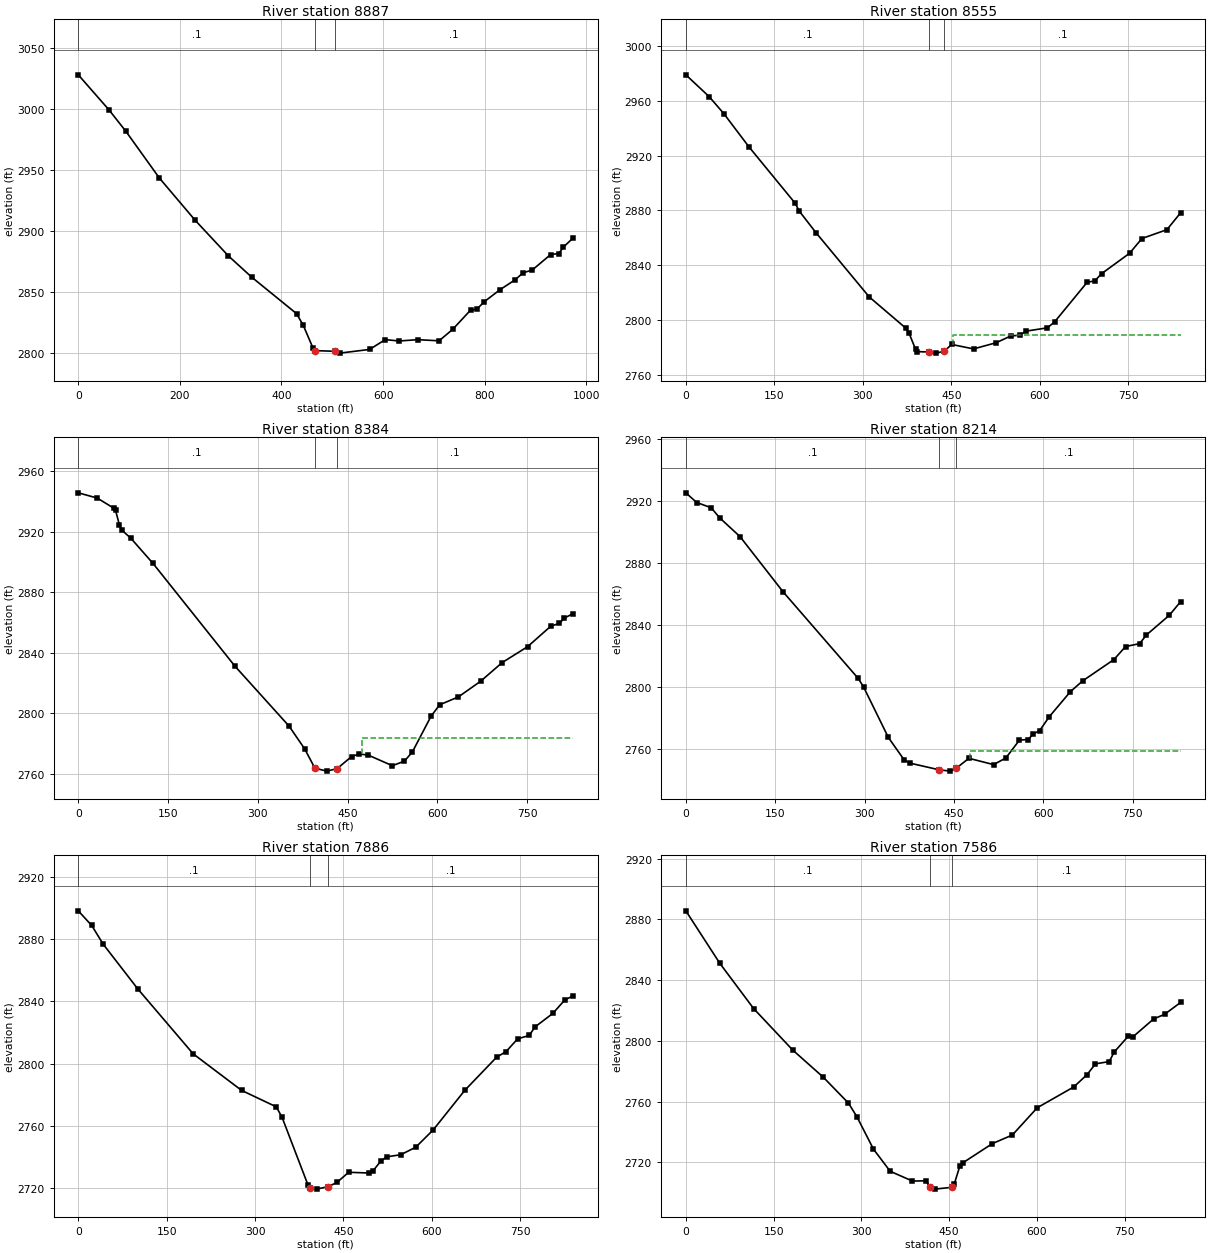
Type RM Length L Ch R = 1 ,8887    ,341.4,331.8,322.1
XS GIS Cut Line= 2
2419049.89413905  699229.23456772418799.78391394698287.787034346
#Sta/Elev= 30
       0 3027.71    60.4 2999.05    93.5 2981.58   159.7 2943.19   229.9 2908.73
   295.5 2879.49   341.8 2861.95   429.6 2832.25   442.7 2822.87   461.8 2804.29
   466.7 2801.95   504.8 2801.42   514.6 2799.91   573.5 2802.93   604.3 2810.97
   631.5 2809.84   668.3 2810.93   710.2 2809.99     737 2819.35   772.2  2835.1
   784.6 2835.86   799.1 2841.96   830.2 2851.83   859.1  2859.7   875.7 2865.64
   893.9 2868.01   929.9 2880.61   946.1 2881.44   954.3 2886.44   974.1 2894.17
#Mann= 3 ,-1 , 0
       0      .1       0   466.7    .045       0   504.8      .1       0
Bank Sta=466.7,504.8
XS Rating Curve= 0 ,0
Exp/Cntr=0.3,0.1

Type RM Length L Ch R = 1 ,8555    ,171.7,171.2,166.6
XS GIS Cut Line= 3
2419462.57996565698842.0748791942419162.26518989698541.854103038
     2418849.117      698271.201
#Sta/Elev= 30
       0 2978.83    39.4 2962.97    64.4 2950.54   106.8 2926.39   185.6 2885.04
   191.6 2879.83   220.3 2863.88   310.8 2816.92   372.3 2794.32   377.9 2790.85
   389.2 2778.82   392.5 2777.07   412.7 2776.76   423.6 2775.97   437.7  2777.3
   450.4  2782.3   487.5 2779.04   525.7 2783.53   550.9 2788.53   565.4 2788.98
   576.7 2792.01   612.7 2794.41   624.9 2798.76     680 2827.59     693 2828.62
   704.4 2833.86   751.8 2848.72   772.9 2859.52   815.2 2865.96   838.5 2878.33
#Mann= 3 ,-1 , 0
       0      .1       0   412.7    .045       0   437.7      .1       0
#XS Ineff= 2 , 0
                          452.75         2788.86
Permanent Ineff=
       F       F
Bank Sta=412.7,437.7
XS Rating Curve= 0 ,0
Exp/Cntr=0.3,0.1

Type RM Length L Ch R = 1 ,8384    ,165.4,170.6,173.8
XS GIS Cut Line= 3
2419607.60770865698685.4937741822419285.68670865698430.634774182
2418954.10570864698179.269774182
#Sta/Elev= 30
       0 2945.77    31.7  2942.3    59.4  2935.6    62.3  2934.1    68.6  2924.7
    72.5 2921.17    87.8 2915.76   124.9 2899.08   261.6 2831.22   352.2 2791.51
   378.3 2776.43   395.4 2763.67   415.4 2761.77   432.5 2763.44   456.5 2771.37
   469.5 2773.13   484.6 2772.34   524.7 2765.35   544.8 2768.36   558.1 2774.41
   589.5 2798.18   603.8 2805.63   635.2 2810.88   672.3 2821.23   708.1 2833.52
   750.6 2844.04   789.4  2857.6   803.7 2859.44   812.2    2863   826.7 2865.93
#Mann= 3 ,-1 , 0
       0      .1       0   395.4    .045       0   432.5      .1       0
#XS Ineff= 2 , 0
                          473.31         2783.89
Permanent Ineff=
       F       F
Bank Sta=395.4,432.5
XS Rating Curve= 0 ,0
Exp/Cntr=0.3,0.1

Type RM Length L Ch R = 1 ,8214    ,330.7,327.8,319.4
XS GIS Cut Line= 2
2419629.96972009698658.0312684582419162.74272009697971.090268458
#Sta/Elev= 30
       0 2925.15    18.3 2918.89    42.5 2915.52      57 2908.91    90.9  2896.9
   162.9 2861.37   289.2 2805.37   298.3 2799.86     340 2767.15   366.6 2752.63
   376.3 2750.56   425.4 2746.24     444  2745.4   453.8 2747.21   475.2 2753.69
   516.6 2749.62   537.2 2753.85   560.1 2765.43   574.7 2765.81   583.3 2769.43
     594 2771.56   610.3  2780.6   645.8 2796.79   666.5 2803.76   718.6 2817.42
   738.3 2825.87   761.8 2827.73   773.3 2833.34   811.7 2846.06   830.8  2854.9
#Mann= 3 ,-1 , 0
       0      .1       0   425.4    .045       0   453.8      .1       0
#XS Ineff= 2 , 0
                          476.58         2758.26
Permanent Ineff=
       F       F
Bank Sta=425.4,453.8
XS Rating Curve= 0 ,0
Exp/Cntr=0.3,0.1

Type RM Length L Ch R = 1 ,7886    ,290.7,300,303.5
XS GIS Cut Line= 3
     2419973.389      698343.998     2419642.536      698110.689
     2419290.676       697854.65
#Sta/Elev= 30
       0 2898.04    22.8 2888.62    42.4 2876.56   101.1 2847.86     195 2806.22
   277.3 2782.72   336.1 2772.19   345.9 2765.48   389.9 2722.03   393.1 2720.16
   404.5 2719.34   424.6 2720.97   439.2 2723.67     459 2730.16   493.6 2729.68
   499.7 2730.79   513.4 2737.24   523.3 2740.06   547.3 2741.42   572.8 2746.23
   602.5 2757.37     656 2782.72   710.4 2804.16   726.1 2807.61   745.9 2815.86
   765.3 2817.99   775.6 2823.57   805.6 2832.17     826 2840.85     840 2843.45
#Mann= 3 ,-1 , 0
       0      .1       0   393.1    .045       0   424.6      .1       0
Bank Sta=393.1,424.6
XS Rating Curve= 0 ,0
Exp/Cntr=0.3,0.1

Type RM Length L Ch R = 1 ,7586    ,302.6,300,292.6
XS GIS Cut Line= 3
2420045.88028258698248.137523754     2419808.455      697881.354
     2419590.073      697535.637
#Sta/Elev= 30
       0 2885.63    58.1 2851.04   115.8 2821.32   182.5 2794.04     235 2776.06
   277.8  2759.1   292.4 2750.07   320.7 2728.73   349.3 2714.15   387.4 2707.71
     411 2707.89   416.8 2704.09   425.3 2702.41   455.1 2703.61   458.8 2705.79
   468.2 2717.43     473 2719.61     524  2732.4   558.1 2738.03   600.7 2756.01
   663.2 2769.71   685.9 2777.83   700.1 2784.89   723.7 2786.38   732.2 2792.67
     756 2803.01   764.7 2802.84   799.6 2814.45   818.3 2817.49   845.8 2825.35
#Mann= 3 ,-1 , 0
       0      .1       0   416.8    .045       0   455.1      .1       0
Bank Sta=416.8,455.1
XS Rating Curve= 0 ,0
Exp/Cntr=0.3,0.1

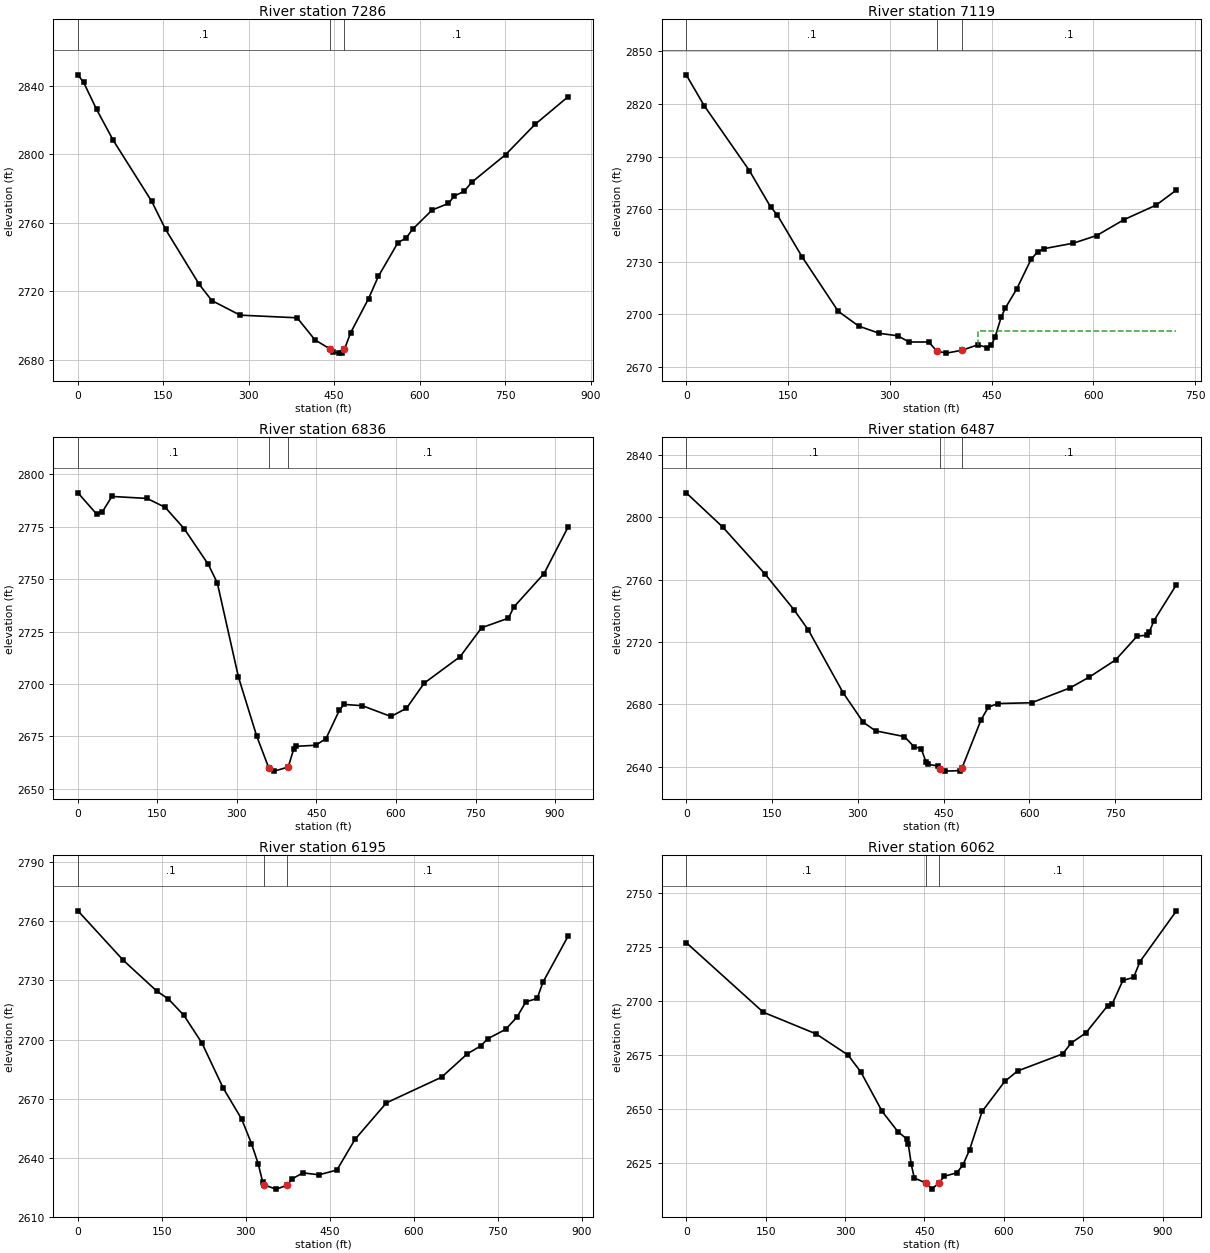
Type RM Length L Ch R = 1 ,7286    ,160.3,166.3,165.5
XS GIS Cut Line= 3
2420350.12767601697977.636339824      2419998.62      697683.616
     2419672.528      697447.712
#Sta/Elev= 30
       0 2846.27      10 2841.86    32.7 2826.17    61.8  2808.2   129.6  2772.5
   153.9 2756.17     213 2724.12     235 2714.71   284.8 2706.19   384.9 2704.65
   416.1 2691.81   442.5  2686.5   447.3 2684.72   458.1 2684.06     463 2684.32
     468 2686.31   478.7 2695.87   510.3 2715.85   527.4 2728.76   561.9 2748.49
   576.1 2751.09   587.6 2756.25     622  2767.5   650.6  2771.3   660.5  2775.6
   677.9 2778.33   691.5 2783.66   750.9 2799.76   802.4 2817.33   860.7 2833.53
#Mann= 3 ,-1 , 0
       0      .1       0   442.5    .045       0     468      .1       0
Bank Sta=442.5,468
XS Rating Curve= 0 ,0
Exp/Cntr=0.3,0.1

Type RM Length L Ch R = 1 ,7119    ,293.6,283.7,284.1
XS GIS Cut Line= 2
2420365.85334461697941.2495891962419955.73249176697346.485581815
#Sta/Elev= 30
       0 2836.56    26.6 2818.92    93.1 2781.96   124.3 2761.28   134.1 2756.76
   170.7 2732.86   223.9 2701.82   254.1 2693.36   284.7 2689.18   311.6 2687.83
   328.4 2684.27   357.6 2684.25   369.2 2679.09   383.5 2677.92   406.5 2679.56
   429.5 2682.63   443.9 2681.11   449.7 2682.37   455.4 2687.31   464.4 2698.67
   470.5 2703.72   487.1 2714.49   508.2 2731.36   517.9 2735.62   526.9 2737.43
   570.5 2740.59     605 2744.95   645.2    2754   692.8 2762.34   722.5  2770.9
#Mann= 3 ,-1 , 0
       0      .1       0   369.2    .045       0   406.5      .1       0
#XS Ineff= 2 , 0
                          430.58         2690.48
Permanent Ineff=
       F       F
Bank Sta=369.2,406.5
XS Rating Curve= 0 ,0
Exp/Cntr(USF)=0,0
Exp/Cntr=0.3,0.1

Type RM Length L Ch R = 1 ,6836    ,365.4,349.2,351.3
XS GIS Cut Line= 3
     2420714.221      697801.546     2420414.906      697556.668
     2419989.757      697227.074
#Sta/Elev= 30
       0 2791.23    35.5 2781.03    45.8 2782.03    64.1 2789.51   130.5 2788.55
   164.7 2784.28   200.5 2774.09     246 2757.04   262.9 2748.27   302.8 2703.31
   336.9 2675.41   359.7 2660.15   370.6 2658.43   396.7 2660.42   407.2 2669.07
   412.2 2670.28   448.4 2670.77     468 2673.95   493.2 2687.52   502.1 2690.26
   536.4 2689.66   590.5  2684.5   619.7 2688.41   653.2 2700.41     721 2713.08
   761.5 2726.86   812.1 2731.42   822.2 2736.73   879.3 2752.72   924.7 2774.95
#Mann= 3 ,-1 , 0
       0      .1       0   359.7    .045       0   396.7      .1       0
Bank Sta=359.7,396.7
XS Rating Curve= 0 ,0
Exp/Cntr=0.3,0.1

Type RM Length L Ch R = 1 ,6487    ,304.6,291.3,284.4
XS GIS Cut Line= 2
     2420846.353      697371.588       2420029.4      697113.073
#Sta/Elev= 30
       0 2815.66      64 2793.65   137.3 2763.76   188.3 2740.71   213.6 2727.63
   274.3 2687.42   309.4 2668.53     331 2663.01   381.4 2659.33   398.2  2652.8
   410.7 2651.66   419.1 2643.09   423.3 2641.48   439.8 2640.55   444.12638.768
   452.7 2637.18   477.9 2637.51   482.1 2639.18   515.6 2670.27   528.2 2678.22
     545 2680.53   603.7 2681.03   670.9 2690.55   704.6 2697.51   750.6 2708.52
   788.3  2723.8   805.1  2724.3   809.3 2726.26   817.7 2733.73   856.9 2756.76
#Mann= 3 ,-1 , 0
       0      .1       0   444.1    .045       0   482.1      .1       0
Bank Sta=444.1,482.1
XS Rating Curve= 0 ,0
Exp/Cntr=0.3,0.1

Type RM Length L Ch R = 1 ,6195    ,145.4,133.4,121.3
XS GIS Cut Line= 2
2420903.34848835696973.5667110652420031.61974917697053.460383698
#Sta/Elev= 30
       0 2765.32    80.9 2740.25   141.2 2724.51   161.3 2720.67   189.4 2712.23
   221.5 2698.22   259.3 2675.47   292.5 2659.59   309.9 2647.23   321.9 2636.99
     330 2627.66   332.9 2626.17   354.1 2624.12   374.2 2626.15   382.2 2629.23
   401.6 2632.37   430.4 2631.39   462.5 2633.81   494.7 2649.34   550.9  2667.9
   649.4 2680.91   695.5  2692.8   719.6 2696.83   731.7 2700.41   763.8 2705.18
   783.9 2711.36   799.9 2719.14     820 2720.84   830.5 2729.14   875.4 2752.52
#Mann= 3 ,-1 , 0
       0      .1       0   332.9    .045       0   374.2      .1       0
Bank Sta=332.9,374.2
XS Rating Curve= 0 ,0
Exp/Cntr(USF)=0,0
Exp/Cntr=0.3,0.1

Type RM Length L Ch R = 1 ,6062    ,231.2,238.7,253.1
XS GIS Cut Line= 4
     2420920.226      696844.3552420550.16702421696857.209092264
2420371.64717235696996.6574339592420047.01663523696941.161478435
#Sta/Elev= 30
       0 2727.19   145.6 2694.93   245.6 2684.87   305.7  2675.1   329.7 2667.33
   370.3 2648.93     400 2639.56   416.7 2636.21   419.5 2633.91   425.2  2624.5
   430.9  2618.1   453.7 2615.71     464 2612.95   477.3 2615.79   487.9 2618.94
   510.7 2620.48   522.5 2623.95   535.5 2631.28   559.1 2648.97   601.8 2662.87
   626.1  2667.7   711.4 2675.64   727.3 2680.66   755.1 2685.35   796.4    2698
   804.7 2698.69     825 2709.66   845.3  2711.1   857.4 2718.42   926.2 2741.93
#Mann= 3 ,-1 , 0
       0      .1       0   453.7    .045       0   477.3      .1       0
Bank Sta=453.7,477.3
XS Rating Curve= 0 ,0
Exp/Cntr=0.3,0.1

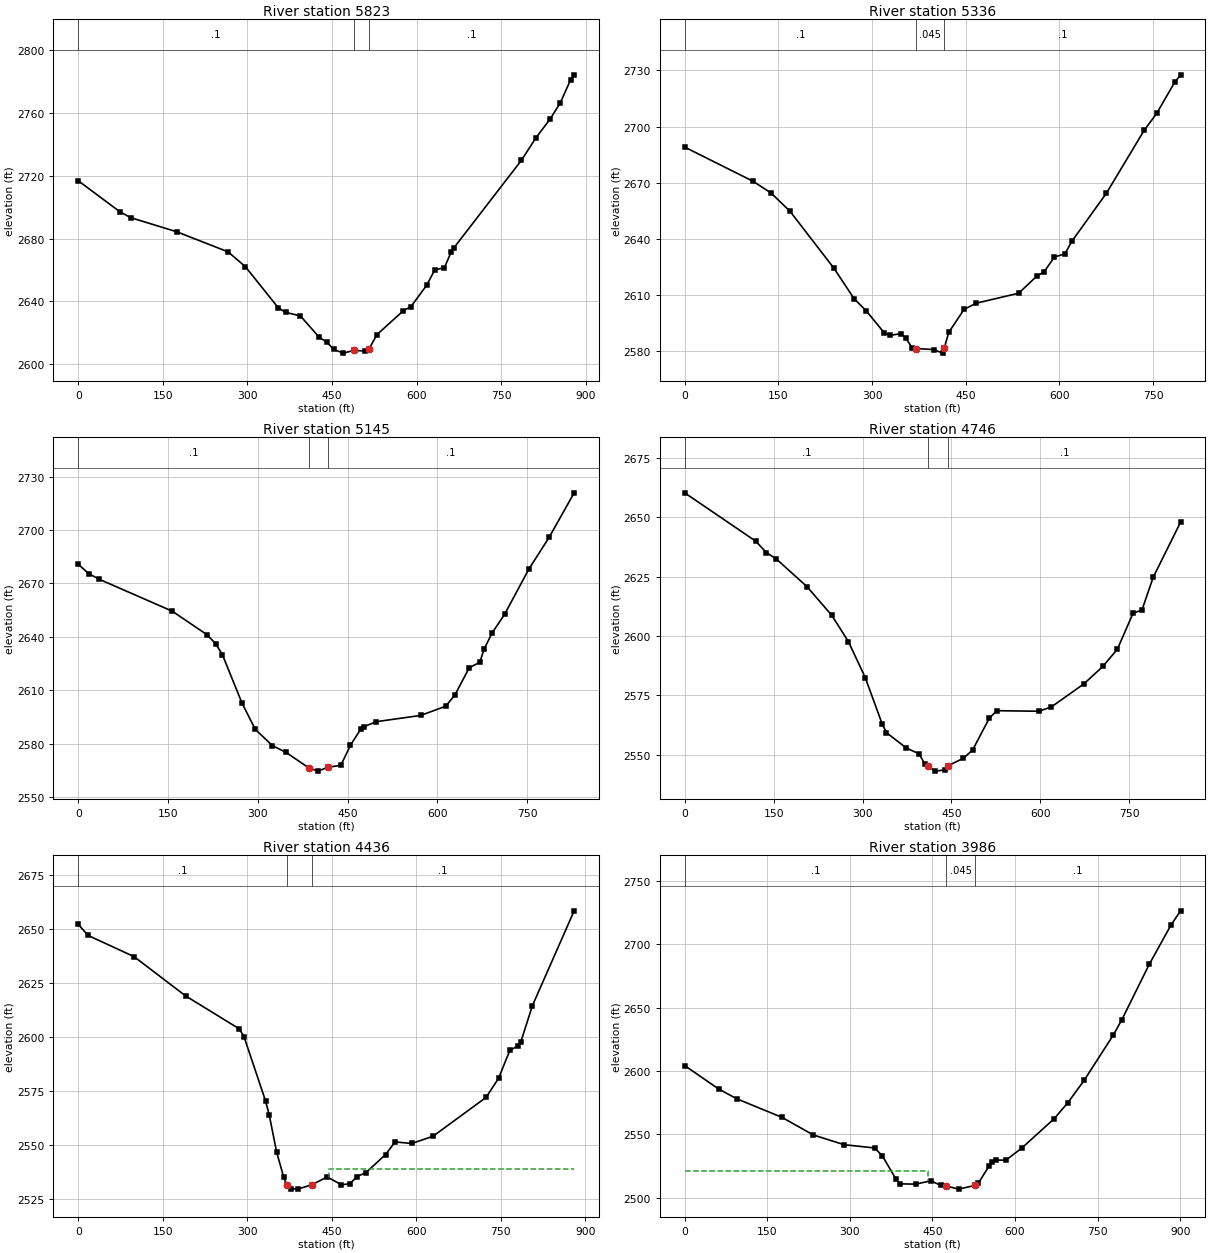
Type RM Length L Ch R = 1 ,5823    ,476.8,487.4,491.4
XS GIS Cut Line= 3
2420899.89470677696826.8657710252420575.04363843696774.104255631
2420059.02625291696582.311645559
#Sta/Elev= 30
       0 2716.91    74.1 2697.09    93.3 2693.37   175.4  2684.3   265.9 2671.57
   296.6  2662.1     355 2635.86   367.8 2633.04   394.1 2630.76   427.6 2617.08
   440.7 2614.19   453.1 2609.39   470.2 2607.05   488.72608.809   508.7 2608.38
   515.4 2609.53     530 2618.91   576.9 2634.14   590.1 2636.67   618.1 2650.35
   632.4 2660.12   649.5  2661.5   661.6 2671.61   666.5 2674.23   786.1 2729.95
   811.6 2744.17   837.2 2756.32     855 2766.53   873.2 2781.17   879.6  2784.4
#Mann= 3 , 0 , 0
       0      .1       0   488.7    .045       0   515.4      .1       0
Bank Sta=488.7,515.4
XS Rating Curve= 0 ,0
Exp/Cntr=0.3,0.1

Type RM Length L Ch R = 1 ,5336    ,188.8,190.6,188.7
XS GIS Cut Line= 2
2420885.51029738696733.0498082552420429.27043275696082.960111408
#Sta/Elev= 30
       0 2689.07   109.3 2670.86   138.5 2664.52   168.8 2654.74     239 2624.39
   271.4 2608.08     291 2601.54   319.4 2589.94     328  2588.5     346 2589.42
   354.5 2586.86   364.3 2581.84   371.1  2581.5   398.5 2580.94   413.1 2579.04
   415.6 2581.59   422.9  2590.1   447.3 2602.37   466.9 2605.71   534.8 2611.03
   563.5 2620.03   575.8 2622.54   592.2 2630.41   608.6 2631.98   620.9 2639.18
   675.5 2664.51   735.9 2698.08   755.9 2707.08   784.5 2723.61   794.2 2727.68
#Mann= 3 ,-1 , 0
       0      .1       0   371.1    .045       0   415.6      .1       0
Bank Sta=371.1,415.6
XS Rating Curve= 0 ,0
Exp/Cntr=0.3,0.1

Type RM Length L Ch R = 1 ,5145    ,400.1,398.8,392.9
XS GIS Cut Line= 2
 2421027.5653028696639.173202921 2420577.0113028695943.760202921
#Sta/Elev= 30
       0 2680.72    18.2 2675.37    35.5 2672.27     157 2654.42   214.8 2641.29
   229.6 2636.17   240.9 2629.98   273.7 2602.78   295.8 2588.05   324.4 2578.94
   347.3 2575.11   385.5 2566.38   400.7  2564.6   417.3 2566.79   438.8 2567.84
   454.9 2579.21   471.9 2588.08     477 2589.53   498.3 2592.37   572.3 2595.88
     614 2601.04   629.5 2607.41   653.3 2622.67   670.9 2625.67   678.3 2633.22
   691.4 2642.12   712.3 2652.59   752.8 2677.99   786.8 2695.85   828.6 2720.86
#Mann= 3 ,-1 , 0
       0      .1       0   385.5    .045       0   417.3      .1       0
Bank Sta=385.5,417.3
XS Rating Curve= 0 ,0
Exp/Cntr=0.3,0.1

Type RM Length L Ch R = 1 ,4746    ,323.1,310.7,300.3
XS GIS Cut Line= 2
2421395.79283801696336.614476246     2420803.153      695746.308
#Sta/Elev= 30
       0 2660.22     120 2639.84   137.7  2635.1   154.7 2632.37   206.5  2620.7
     248  2608.7   276.3 2597.58   304.6 2582.47   332.9 2563.12   340.2 2559.36
   374.1 2552.81   395.1 2550.47   404.9 2546.26   410.5 2545.29   421.9 2543.14
   438.9 2543.61   444.5 2545.44   470.1 2548.56   485.6    2552   513.9 2565.45
   526.5 2568.57   597.6 2568.33   618.6 2570.17   673.3 2579.83   705.3 2587.18
   729.8 2594.42   756.3 2609.59   771.3 2610.92   790.3 2624.71   836.5 2647.93
#Mann= 3 ,-1 , 0
       0      .1       0   410.5    .045       0   444.5      .1       0
Bank Sta=410.5,444.5
XS Rating Curve= 0 ,0
Exp/Cntr=0.3,0.1

Type RM Length L Ch R = 1 ,4436    ,431.5,450,448.2
XS GIS Cut Line= 3
     2421694.215      695940.943     2421312.314      695834.697
     2420852.973        695683.1
#Sta/Elev= 30
       0 2652.24    17.5  2647.1    99.1 2637.26   190.4 2619.09   285.9 2603.76
   294.2 2600.16   332.6 2570.25   339.1 2563.74     352 2546.74   364.8  2534.9
   370.2 2531.36   377.3 2529.67   389.7 2529.47   414.9 2531.53   441.8 2535.13
   467.2 2531.47   482.3    2532   494.9 2535.32   510.7 2537.13   545.5 2545.52
   562.3 2551.36   591.8 2550.63   629.7 2553.99   723.7 2571.98   745.9 2580.81
   765.9 2593.78   780.7 2595.92   785.6 2597.86     806 2614.52   880.1  2658.5
#Mann= 3 ,-1 , 0
       0      .1       0   370.2    .045       0   414.9      .1       0
#XS Ineff= 2 , 0
                          444.44         2538.98
Permanent Ineff=
       F       F
Bank Sta=370.2,414.9
XS Rating Curve= 0 ,0
Exp/Cntr=0.3,0.1

Type RM Length L Ch R = 1 ,3986    ,610,620.3,618.9
XS GIS Cut Line= 3
     2421732.276      695662.878     2421288.809      695402.471
2420947.69175842695220.910708896
#Sta/Elev= 30
       0 2604.37    62.1 2585.74    94.6 2578.13   176.5  2563.5   233.7 2549.55
   289.4 2541.88     345 2539.29     359 2533.06     384  2514.5   391.4 2510.93
   419.3 2510.73   447.1 2513.31   465.6 2509.69   474.9 2509.26   497.6 2506.78
   527.3 2509.76   533.2  2511.3   552.9 2525.13     559  2528.2   565.8 2529.71
   583.5  2529.7   611.8 2539.03   670.7 2562.26   695.9 2575.04   725.5 2592.67
   778.7 2628.68   793.5 2640.17   843.7 2684.31   883.6 2715.64   900.7 2726.58
#Mann= 3 ,-1 , 0
       0      .1       0   474.9    .045       0   527.3      .1       0
#XS Ineff= 2 , 0
          441.99 2520.79
Permanent Ineff=
       F       F
Bank Sta=474.9,527.3
XS Rating Curve= 0 ,0
Exp/Cntr=0.3,0.1