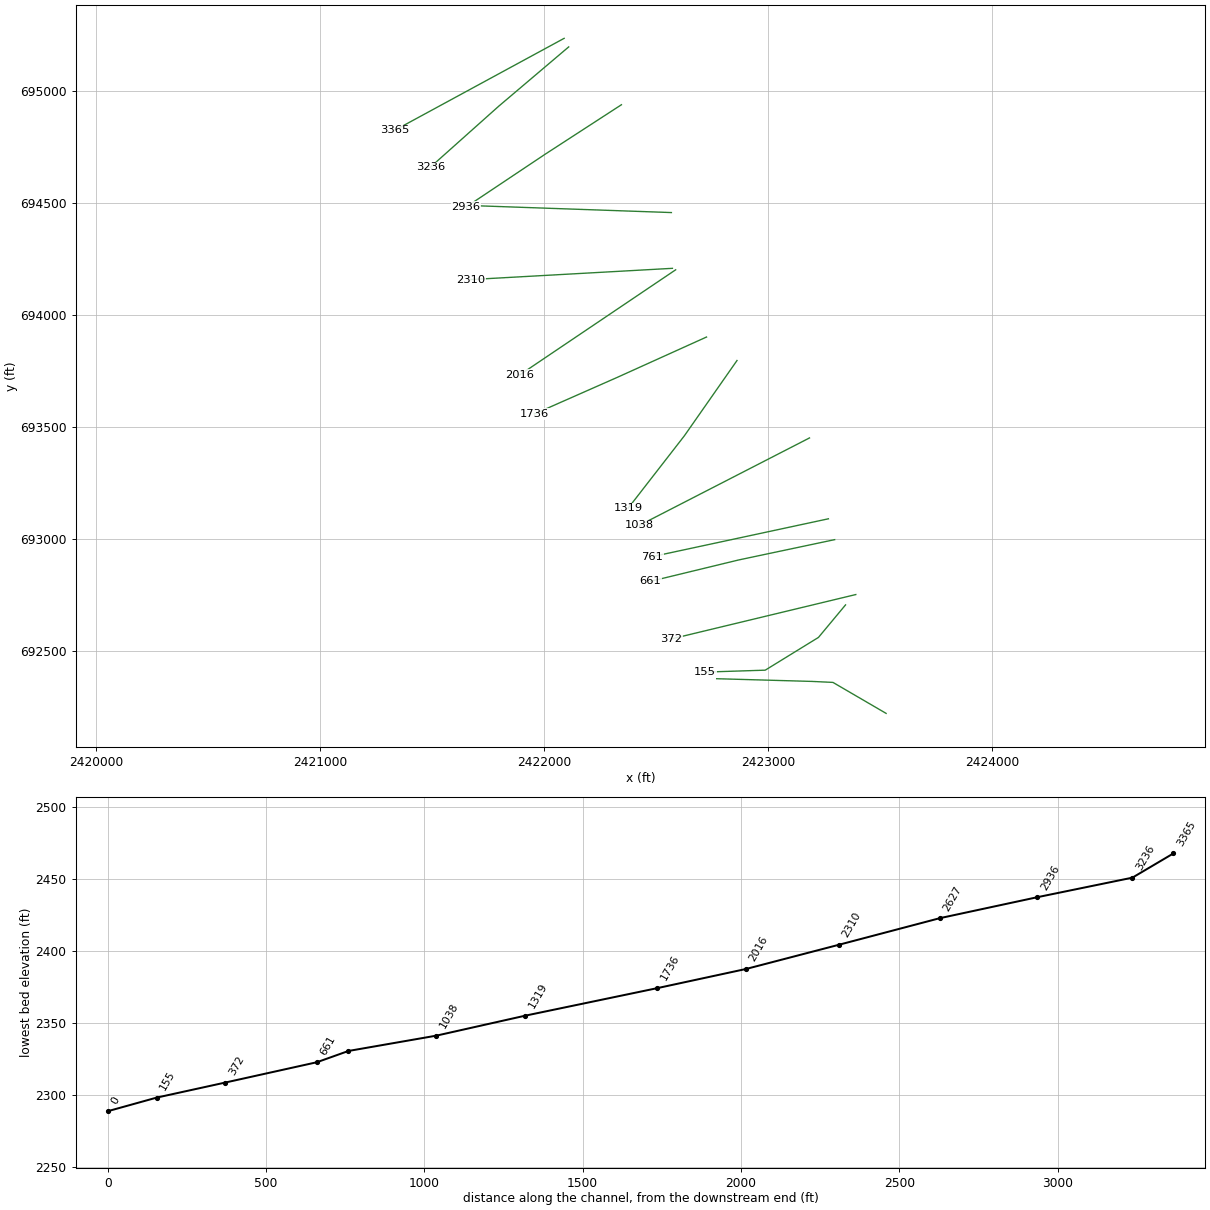
HEC-RAS study LONGRN.prj: LONGRN

--- LONGRN.g01 (geometry) --- (continued)

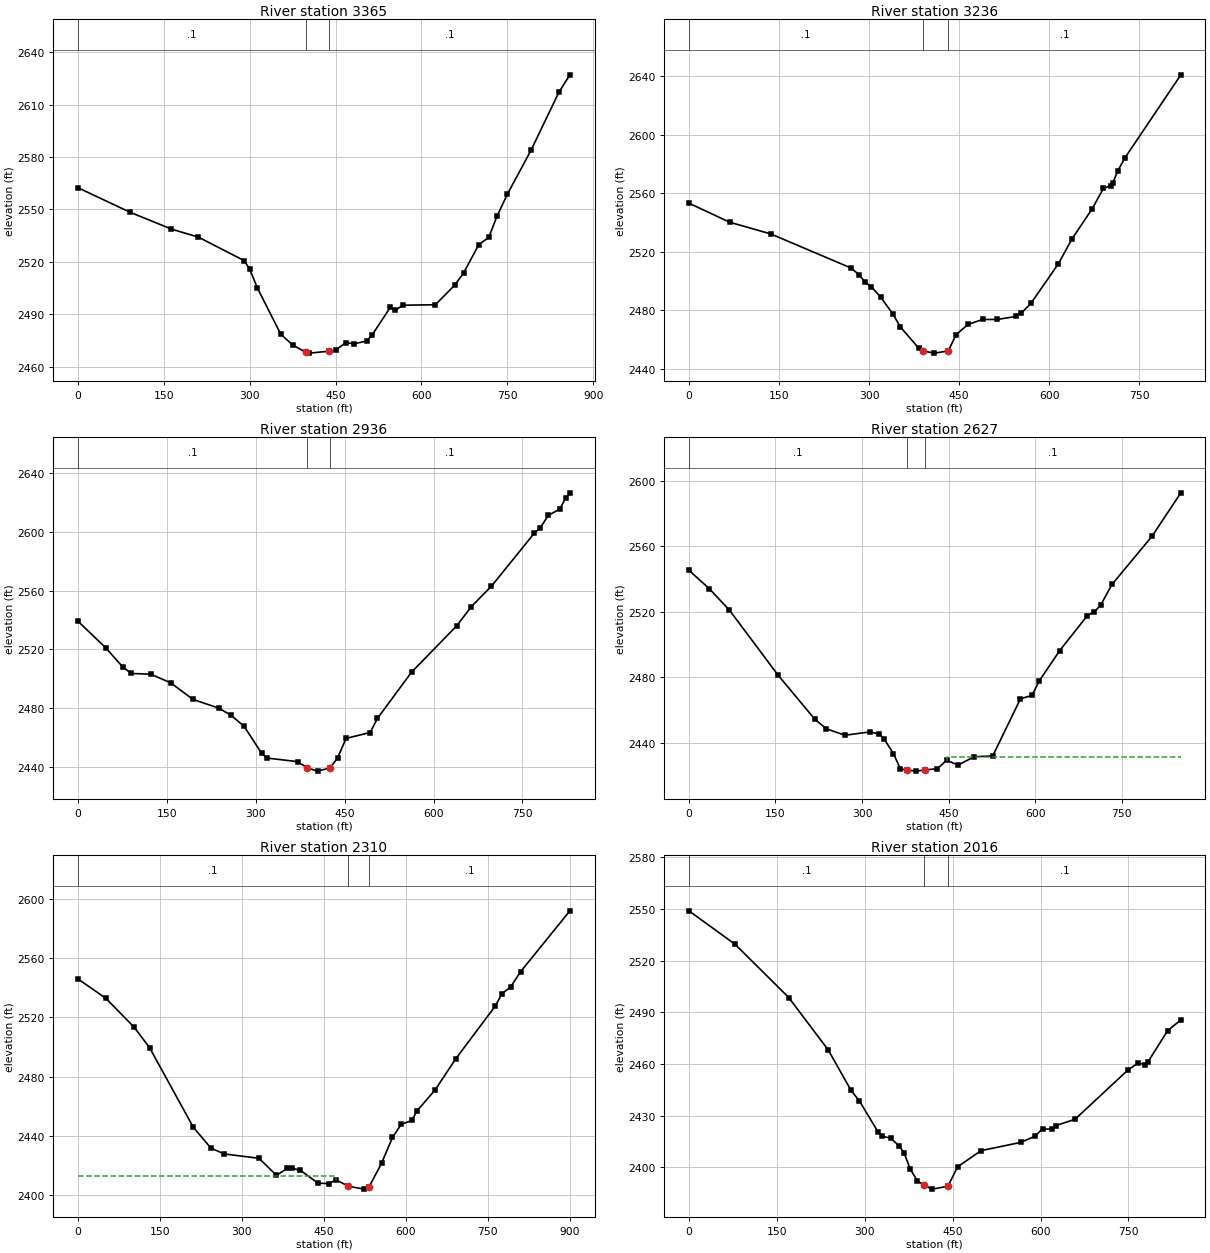
Type RM Length L Ch R = 1 ,3365    ,124,129.7,133.1
XS GIS Cut Line= 2
2422090.13467076695236.6776168572421334.77700266694826.701954662
#Sta/Elev= 30
       0  2562.4    90.3 2548.43   163.1 2538.72   210.3  2534.1     290 2520.69
   299.7 2515.98   313.3 2505.02   354.3 2478.45   375.5 2472.19   397.9 2468.17
   404.4 2467.66   438.62468.758   449.9 2469.34   468.1 2473.72   481.7    2473
   504.5 2474.56   513.6 2477.92   545.4 2493.81   554.6 2492.36   568.2 2495.11
   624.3 2495.37   657.8 2506.45   673.5 2513.46     700 2529.72   717.7 2533.97
     732 2546.08     750  2558.6   791.5 2583.88   840.1 2617.06   859.4 2627.06
#Mann= 3 , 0 , 0
       0      .1       0   397.9    .045       0   438.6      .1       0
Bank Sta=397.9,438.6
XS Rating Curve= 0 ,0
Exp/Cntr=0.3,0.1

Type RM Length L Ch R = 1 ,3236    ,302.1,300,297.2
XS GIS Cut Line= 3
     2422110.561      695198.481     2421798.017      694933.643
     2421492.483      694661.034
#Sta/Elev= 30
       0 2553.18    67.9 2540.14   136.1  2532.2   269.2 2509.04   283.4 2504.37
   293.4 2499.15   303.8 2496.18   319.6 2488.86   339.7 2477.48     352 2468.75
   382.5  2454.3   389.2 2452.35   408.3 2450.81   431.8 2452.27   445.1  2463.5
   464.9 2470.43   489.1 2473.78   513.1 2473.78   544.2 2475.82   553.4 2478.01
     570 2485.08   615.1 2511.73   637.7 2528.62   671.4 2549.27   690.2 2563.19
   702.9 2565.22   705.7  2566.8   714.2 2575.36   726.2 2584.16   819.1 2640.76
#Mann= 3 ,-1 , 0
       0      .1       0   389.2    .045       0   431.8      .1       0
Bank Sta=389.2,431.8
XS Rating Curve= 0 ,0
Exp/Cntr=0.3,0.1

Type RM Length L Ch R = 1 ,2936    ,316.9,308.3,299.4
XS GIS Cut Line= 3
     2422345.951      694940.232     2422004.453      694718.639
     2421652.547      694483.666
#Sta/Elev= 30
       0 2539.11    46.7 2521.09    75.3 2508.15    89.7 2503.63     123 2503.12
   156.4 2497.25   194.1    2486   237.5 2480.06   257.8 2475.38   280.4 2467.67
   309.8 2449.47   318.4 2446.17   370.6  2443.7   386.6 2439.52   404.4 2437.25
   425.4 2439.45     438 2446.14   452.4  2459.5   493.1  2463.5   505.3 2473.06
   563.1 2504.58   638.9  2535.9   664.1 2549.14   697.7 2562.91   769.9 2598.87
   780.2 2602.66   793.9 2611.12   813.2 2615.35   822.8 2622.85   830.2  2626.4
#Mann= 3 ,-1 , 0
       0      .1       0   386.6    .045       0   425.4      .1       0
Bank Sta=386.6,425.4
XS Rating Curve= 0 ,0
Exp/Cntr=0.3,0.1

Type RM Length L Ch R = 1 ,2627    ,316.1,317.8,322.7
XS GIS Cut Line= 2
     2422568.948      694458.716 2421716.9966285694488.511716939
#Sta/Elev= 30
       0 2545.31    35.3 2534.08    70.2 2520.99   154.3 2481.37   218.3 2454.29
   238.3  2448.5   270.4 2444.58   313.2 2446.58   329.8 2445.34   338.1 2442.39
   354.4  2433.4   366.4 2424.09   378.4 2423.22   394.4 2422.66   408.4 2423.35
   430.5 2424.14   446.5 2429.27   466.5 2426.42   494.5 2431.44   526.5 2431.93
   574.6 2466.83   594.6 2468.91   606.6 2477.46   642.6 2496.27   690.6 2517.66
   702.6 2519.87   713.9 2524.23   733.2 2536.67   802.6 2566.11   852.5 2592.62
#Mann= 3 ,-1 , 0
       0      .1       0   378.4    .045       0   408.4      .1       0
#XS Ineff= 2 , 0
                          447.48         2431.34
Permanent Ineff=
       F       F
Bank Sta=378.4,408.4
XS Rating Curve= 0 ,0
Exp/Cntr=0.3,0.1

Type RM Length L Ch R = 1 ,2310    ,281.2,293.3,299.1
XS GIS Cut Line= 2
2422573.54206909694209.7308444512421674.33189657694159.569723645
#Sta/Elev= 30
       0 2545.83    50.9 2532.81     103 2513.24     131 2499.54   211.1 2445.93
   243.2 2431.96   267.2 2427.97   331.3 2425.03   363.4 2413.55   383.4 2418.23
   391.4 2418.49   407.3 2416.86   439.5 2408.22   459.5 2407.96   472.1 2410.54
   494.8 2406.23   523.6 2404.24   532.8  2405.7   555.7  2421.6   575.7 2439.03
   591.7 2447.87   611.7 2450.59   619.8 2456.63   653.4 2470.86   691.5 2491.99
     764 2527.59     776 2535.82     792 2540.39   810.3 2550.73   900.6 2591.74
#Mann= 3 ,-1 , 0
       0      .1       0   494.8    .045       0   532.8      .1       0
#XS Ineff= 2 , 0
          472.96 2412.89
Permanent Ineff=
       F       F
Bank Sta=494.8,532.8
XS Rating Curve= 0 ,0
Exp/Cntr=0.3,0.1

Type RM Length L Ch R = 1 ,2016    ,279,280.6,270
XS GIS Cut Line= 2
     2422587.968      694203.093     2421892.007      693733.966
#Sta/Elev= 30
       0 2548.81    78.7 2529.41   170.3 2498.53   237.8 2468.06   276.4 2444.81
   290.9 2438.53   322.4 2420.74   329.5 2418.09     344 2417.02     359 2412.45
     367 2408.49   377.7 2398.96     390  2392.1   401.9 2389.58   415.4 2387.42
   441.9 2389.09   458.4 2400.32   498.3 2409.73   565.9 2414.51     590    2418
   603.3 2422.35   618.9 2422.18   626.3 2424.29   658.7  2427.9   749.2 2456.53
   766.1 2460.46   778.1 2459.68   782.9 2461.01   816.7 2479.27   839.3 2485.55
#Mann= 3 ,-1 , 0
       0      .1       0   401.9    .045       0   441.9      .1       0
Bank Sta=401.9,441.9
XS Rating Curve= 0 ,0
Exp/Cntr=0.3,0.1

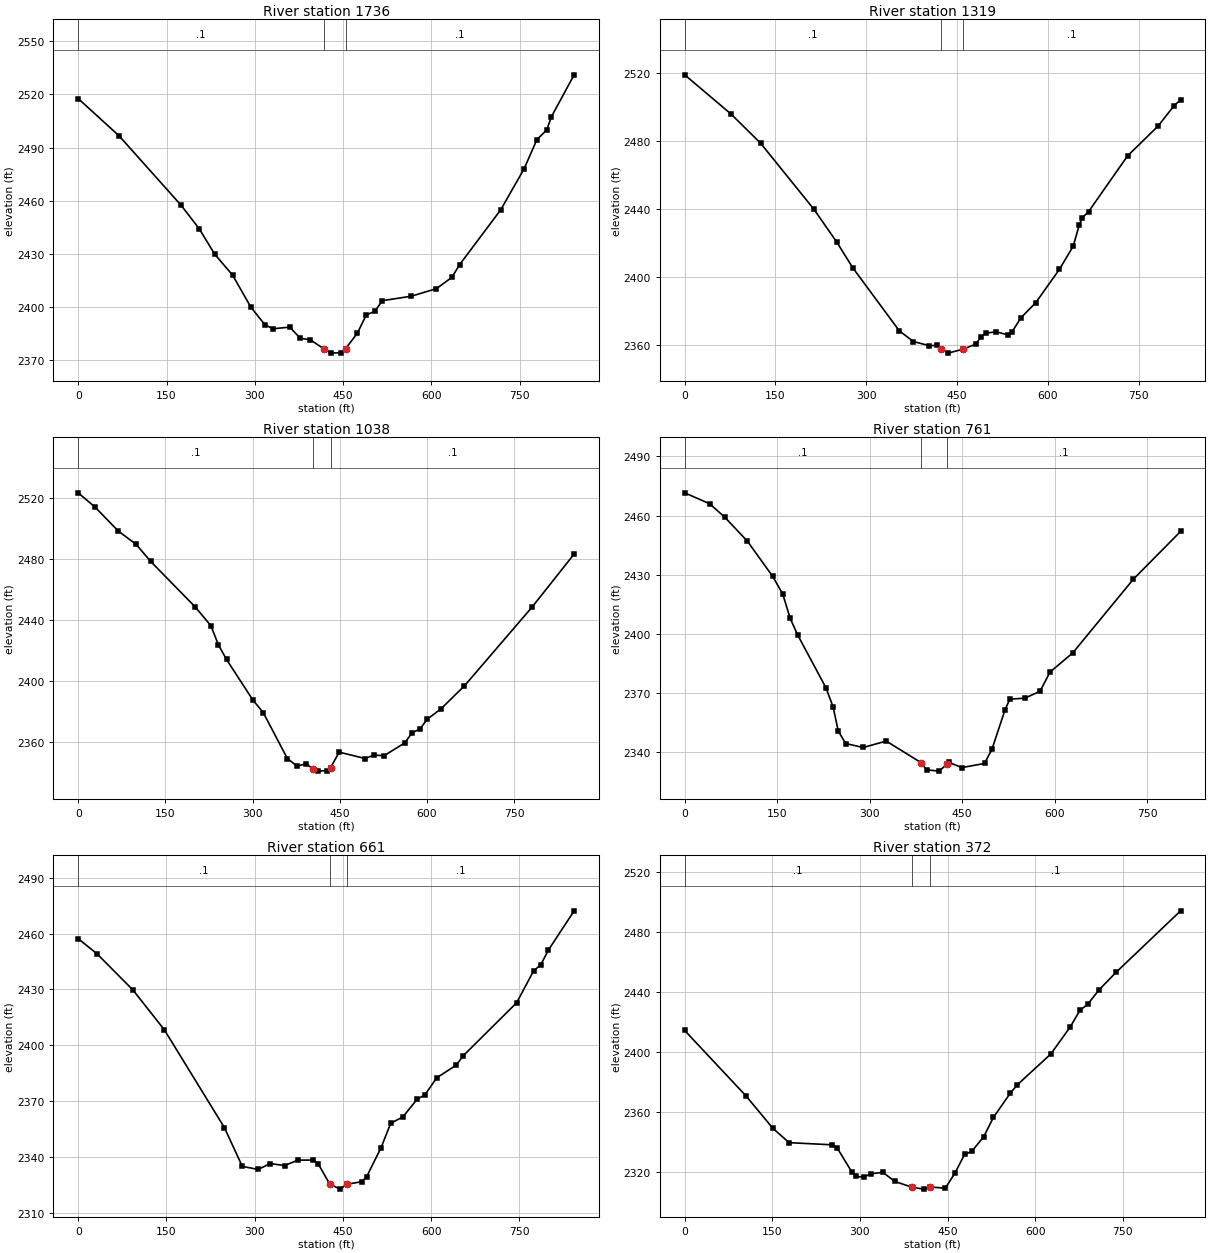
Type RM Length L Ch R = 1 ,1736    ,405.1,416.9,422.3
XS GIS Cut Line= 3
     2422725.866      693902.991     2422327.489      693722.901
     2421956.931      693559.294
#Sta/Elev= 30
       0  2517.6    69.3 2496.65   174.8 2457.44   205.4 2444.27   231.7 2429.94
   262.4 2417.97   293.1 2400.06   316.8 2390.21   330.4 2387.83   359.2 2388.74
   377.3 2382.46   394.1 2381.63   417.8 2376.39   429.2 2374.09   446.9 2374.36
   454.3 2376.69   474.2 2385.38   489.3 2395.69   503.6 2397.59   516.6 2403.67
     566  2406.2   608.5 2410.47   634.8 2416.88   647.9 2424.04   717.8 2455.01
   757.2 2477.97   779.1 2494.52   795.7 2499.89   803.6 2507.33   842.3 2531.01
#Mann= 3 ,-1 , 0
       0      .1       0   417.8    .045       0   454.3      .1       0
Bank Sta=417.8,454.3
XS Rating Curve= 0 ,0
Exp/Cntr=0.3,0.1

Type RM Length L Ch R = 1 ,1319    ,284.4,280.5,270.4
XS GIS Cut Line= 3
2422861.95946546693798.1091381772422627.10946546693462.093138178
2422375.94246546693138.749138177
#Sta/Elev= 30
       0 2518.88    76.4 2495.84   125.3 2478.66   213.8 2439.58   251.7 2420.13
   277.5 2405.35   354.7 2368.06     378 2361.79   404.1 2359.36   417.1 2359.54
   423.9 2357.28   435.3 2354.97   459.6 2357.27   480.9 2360.26   489.5 2364.54
     498 2366.78   514.9 2367.48   534.4 2365.72   540.8  2367.5   555.8 2375.87
   580.1 2384.71   619.2 2404.35   641.9 2417.94   652.1 2430.66   657.1 2434.79
   667.3  2438.3   731.8 2471.16   782.2  2488.7   808.7 2500.78   819.4 2504.09
#Mann= 3 ,-1 , 0
       0      .1       0   423.9    .045       0   459.6      .1       0
Bank Sta=423.9,459.6
XS Rating Curve= 0 ,0
Exp/Cntr=0.3,0.1

Type RM Length L Ch R = 1 ,1038    ,279.4,277.8,271.9
XS GIS Cut Line= 2
2423185.68796565693452.4000860632422426.94777576693062.583758785
#Sta/Elev= 30
       0 2523.13    29.6 2513.55    68.7  2498.2    99.6 2489.43   124.7 2478.24
   201.2  2448.5   228.2 2436.22     241  2423.8   255.1 2414.14   300.4 2387.61
   318.2 2379.42   359.8 2349.29   376.6 2344.38   392.5 2345.98   403.5 2342.44
   412.5  2341.1   428.1 2341.47   434.1 2343.35   448.9 2353.52   493.5 2349.34
   508.3 2351.58   526.2 2351.19   561.8 2359.61   574.4 2366.22   587.9  2368.7
   600.4 2375.07   623.9 2381.83   664.4 2396.91   781.3  2448.7     853 2483.12
#Mann= 3 ,-1 , 0
       0      .1       0   403.5    .045       0   434.1      .1       0
Bank Sta=403.5,434.1
XS Rating Curve= 0 ,0
Exp/Cntr=0.3,0.1

Type RM Length L Ch R = 1 ,761     ,103.4,99.6,100.3
XS GIS Cut Line= 2
2423270.15057955693091.3379144762422483.76964779692922.363499387
#Sta/Elev= 30
       0 2471.54    40.3 2466.03    64.9 2459.22   101.7 2447.03   142.6 2429.23
     159 2420.24   171.2 2407.84   183.5 2399.32   228.9 2372.84   240.8 2362.92
   249.1 2350.72   261.2 2344.43   289.5 2342.43   326.9 2345.68   383.8 2334.67
   392.2 2331.11   412.6 2330.45   424.9 2333.83     429 2334.86   449.4 2332.24
   486.3 2334.34   498.3 2341.53   519.7 2361.66   527.2 2366.91   552.2 2367.46
   576.3 2370.96   592.6 2380.69   629.5 2390.43   727.6 2427.73   804.3 2451.99
#Mann= 3 , 0 , 0
       0      .1       0   383.8    .045       0   424.9      .1       0
Bank Sta=383.8,424.9
XS Rating Curve= 0 ,0
Exp/Cntr(USF)=0,0
Exp/Cntr=0.3,0.1

Type RM Length L Ch R = 1 ,661     ,290.4,288.8,290.4
XS GIS Cut Line= 3
2423298.08161382692998.2203170942422868.61461382692907.368317093
2422475.69361382692812.129317094
#Sta/Elev= 30
       0 2457.31      32 2449.16    93.4 2429.59   146.5 2408.28   248.6  2355.7
     279 2334.86     306 2333.22   326.4 2336.39   350.9 2335.29   373.5 2338.23
     400 2338.24   408.2 2336.11   427.5 2325.49     445 2322.63   457.4 2325.32
   482.1  2326.6   490.3 2329.22     515 2344.94   531.4  2358.1     552 2361.43
   576.7 2371.13   589.1 2373.14   609.6 2382.49   642.6 2389.26   654.9 2394.41
   745.5 2422.86   774.3 2439.94   786.6 2443.31   799.4 2451.12   843.3 2472.28
#Mann= 3 ,-1 , 0
       0      .1       0   427.5    .045       0   457.4      .1       0
Bank Sta=427.5,457.4
XS Rating Curve= 0 ,0
Exp/Cntr=0.3,0.1

Type RM Length L Ch R = 1 ,372     ,209.9,216.9,219.9
XS GIS Cut Line= 2
2423392.45117807692753.0985120382422567.21724376692554.482887168
#Sta/Elev= 30
       0 2414.19   104.6 2370.78     151 2349.02   178.7  2339.5   252.7 2338.04
     261    2336   285.6 2320.24   293.9    2317   306.2  2316.5   318.5 2318.73
   339.1 2319.71   359.7 2313.67   388.5 2309.85   409.1 2308.54   419.7 2309.95
   446.1 2309.18   462.5 2319.18     479 2331.62   491.3 2333.62   511.9 2343.54
   528.4 2356.28     557  2372.3   569.5 2378.08   626.7 2398.56     660 2416.62
   676.4 2427.59   689.7  2431.6   709.1 2441.19   738.2 2452.88   848.8 2493.88
#Mann= 3 ,-1 , 0
       0      .1       0   388.5    .045       0   419.7      .1       0
Bank Sta=388.5,419.7
XS Rating Curve= 0 ,0
Exp/Cntr(USF)=0,0
Exp/Cntr=0.3,0.1

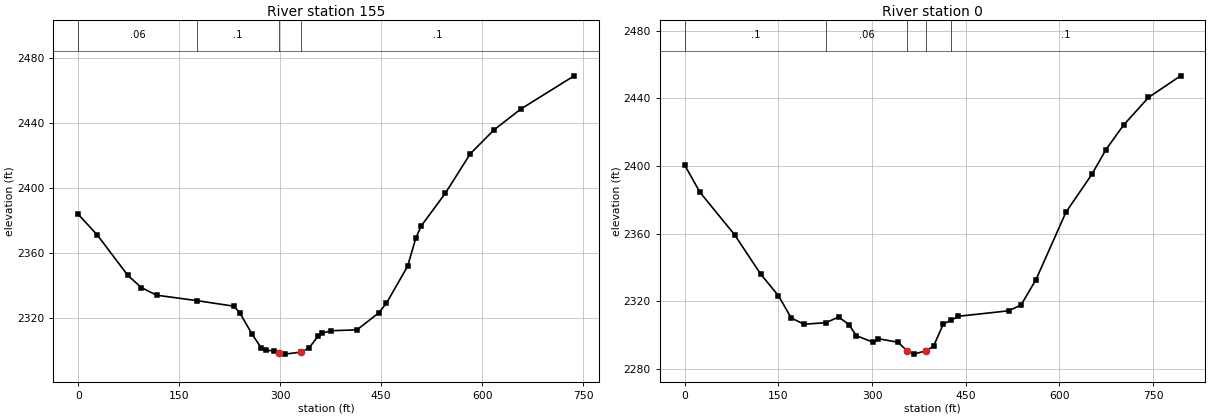
Type RM Length L Ch R = 1 ,155     ,132.9,155.1,132.9
XS GIS Cut Line= 4
2423346.57382945692706.9075409552423225.82101672692561.760220607
2422987.97456741692415.3931748782422719.63498358 692406.85509721
#Sta/Elev= 30
       0 2383.83    28.3 2371.17    73.7 2346.37    93.7 2338.92   116.3 2334.23
     176 2330.91   230.9 2327.49   239.7 2323.59   258.2 2310.31   271.6 2302.07
   278.2 2300.32   291.1 2300.18   298.32298.873   306.5 2298.07   331.1 2299.31
   342.7  2301.8   356.8 2309.35   361.5 2310.81   375.6 2312.41   414.1 2312.97
   446.1 2323.29   457.7 2329.22   489.3 2352.04   501.3 2369.09   509.3 2376.61
   545.4 2396.82   582.2 2420.91   617.6 2435.65   657.4 2448.41   736.6 2468.78
#Mann= 4 ,-1 , 0
       0     .06       0     176      .1       0   298.3    .045       0
   331.1      .1       0
Bank Sta=298.3,331.1
XS Rating Curve= 0 ,0
Exp/Cntr(USF)=0,0
Exp/Cntr=0.3,0.1

Type RM Length L Ch R = 1 ,0       ,,,
XS GIS Cut Line= 4
2423527.68982637692222.4890393612423290.35876885692360.781206399
2423197.69999999692365.1560000032422771.26154664692377.274261966
#Sta/Elev= 30
       0 2400.57    24.2 2384.55    79.8 2359.33   121.5 2336.07   150.2 2323.13
   170.6    2310   190.9 2306.28   226.2 2307.22   246.5 2310.55     263 2306.11
   274.7 2299.52   302.3 2295.55   310.3 2297.68   341.3 2295.67   356.1 2290.58
   366.4 2288.59   386.4 2290.53   398.4 2293.25   414.4 2306.62   426.4 2308.56
   438.4 2311.02   518.5 2314.23   538.5 2317.66   562.5  2332.7   610.5 2372.67
   652.2 2395.18   674.5  2409.7   702.7  2424.2   742.6 2440.55794.0556 2453.37
#Mann= 5 ,-1 , 0
       0      .1       0   226.2     .06       0   356.1    .045       0
   386.4     .06       0   426.4      .1       0
Bank Sta=356.1,386.4
XS Rating Curve= 0 ,0
Exp/Cntr(USF)=0,0
Exp/Cntr=0.3,0.1
LCMann Table=0

Chan Stop Cuts=-1
Use User Specified Reach Order=0
Composite Channel Slope=5